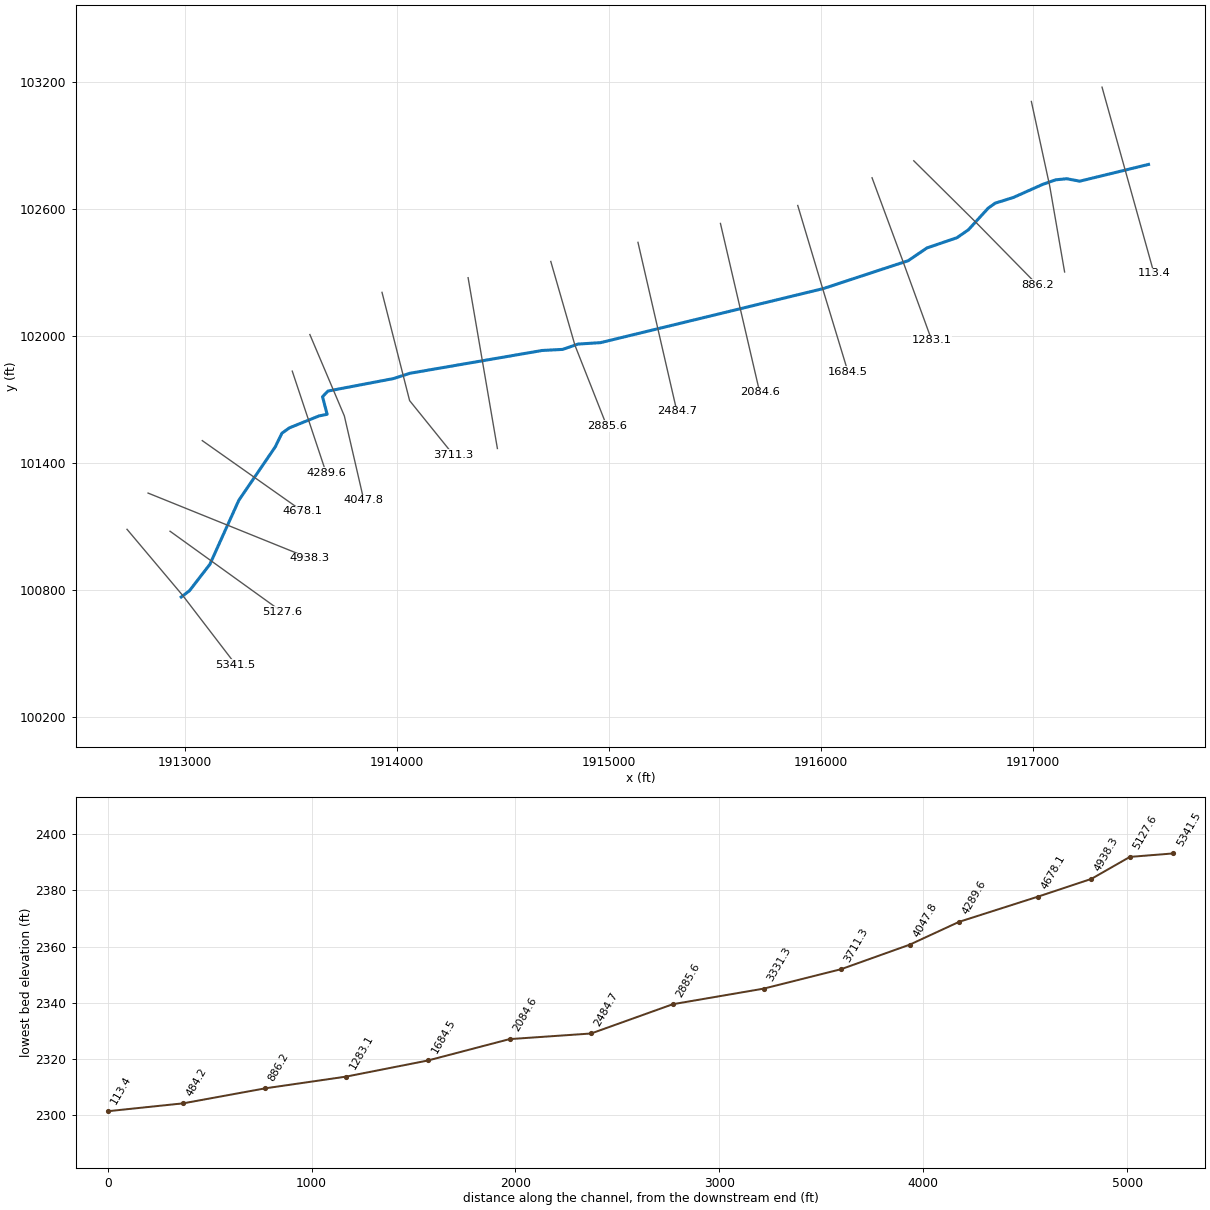
--- GrssyBrnch.prj (project) ---

Proj Title=GrssyBrnch
Current Plan=p01
Default Exp/Contr=0,0
English Units
Geom File=g01
Flow File=f01
Plan File=p01
BEGIN DESCRIPTION:
END DESCRIPTION:
DSS Export Rating Curves= 0
DSS Export Rating Curve Sorted= 0
DSS Export Volume Flow Curves= 0
DXF OffsetX= 0
DXF OffsetY= 0
DXF ScaleX= 0
DXF ScaleY= 0

--- GrssyBrnch.p01 (plan) ---

Plan Title=Floodplain
Program Version=4.00
Geom File=g01
Flow File=f01
K Sum by GR=0
Std Step Tol=0.01
Critical Tol=0.01
Num of Std Step Trials=20
Max Error Tol=0.3
Flow Tol Ratio=0.001
Split Flow NTrial=30
Split Flow Tol=0.02
Split Flow Ratio=0.02
Log Output Level=0
Friction Slope Method=1
Unsteady Friction Slope Method=2
Unsteady Bridges Friction Slope Method=1
Global Log Level=0
CheckData=False
Run HTab=0
Run UNet=0
Run PostProcess=0
UNET Theta=0
UNET Theta Warmup=0
UNET ZTol=0
UNET ZSATol=0
UNET MxIter=0
UNET MaxInSteps=0
UNET DtIC=0
UNET DtMin=0
UNET MaxCRTS=0
UNET WFStab=0
UNET SFStab=0
UNET WFX=0
UNET SFX=0
UNET DSS MLevel=0
UNET DZMax Abort=0
UNET Convert EG Bridges=0
UNET Use Existing IB Tables=0
UNET Froude Limit=0
UNET Froude Power=0
Write IC File=0
Echo Input=False
Echo Output=False
Write Detailed=0

--- GrssyBrnch.f01 (steady flow) ---

Flow Title=NFF Regression Equation
Program Version=4.10
Number of Profiles= 1
Profile Names=P100yr
River Rch & RM=GrssyBrnch,Main            ,5341.5
341.3454
River Rch & RM=GrssyBrnch,Main            ,4678.1
345.9272
River Rch & RM=GrssyBrnch,Main            ,4289.6
637.8743
River Rch & RM=GrssyBrnch,Main            ,2885.6
674.9006
River Rch & RM=GrssyBrnch,Main            ,113.4
739.9322
Boundary for River Rch & Prof#=GrssyBrnch,Main            , 1
Up Type= 0
Dn Type= 1
Dn Known WS=2305.15
DSS Import GetInterval= 0
DSS Import GetPeak= 0
DSS Import FillOption= 0

--- GrssyBrnch.g01 (geometry) ---

Geom Title=USGS 3m DEM
Program Version=4.10

River Reach=GrssyBrnch      ,Main
Reach XY= 30
     1912982.961      100766.915     1913021.548      100796.423
     1913117.902      100921.423     1913254.173       101223.67
     1913426.598      101477.002     1913457.486       101540.96
     1913493.274      101566.523     1913632.591      101622.761
     1913670.936       101630.43     1913649.207      101713.509
      1913674.77       101740.35     1913982.842      101799.115
     1914061.676      101824.356     1914684.504      101932.072
     1914781.643      101937.184     1914853.981      101962.267
     1914960.583      101969.138     1916011.426      102224.754
     1916411.277      102356.416     1916499.469      102416.488
     1916641.343      102465.058     1916695.025      102502.124
     1916789.378      102605.471     1916822.185       102628.47
     1916907.677      102655.302     1917045.237      102716.852
     1917106.588      102738.581     1917158.992      102743.693
     1917220.342       102732.19     1917544.991      102811.435

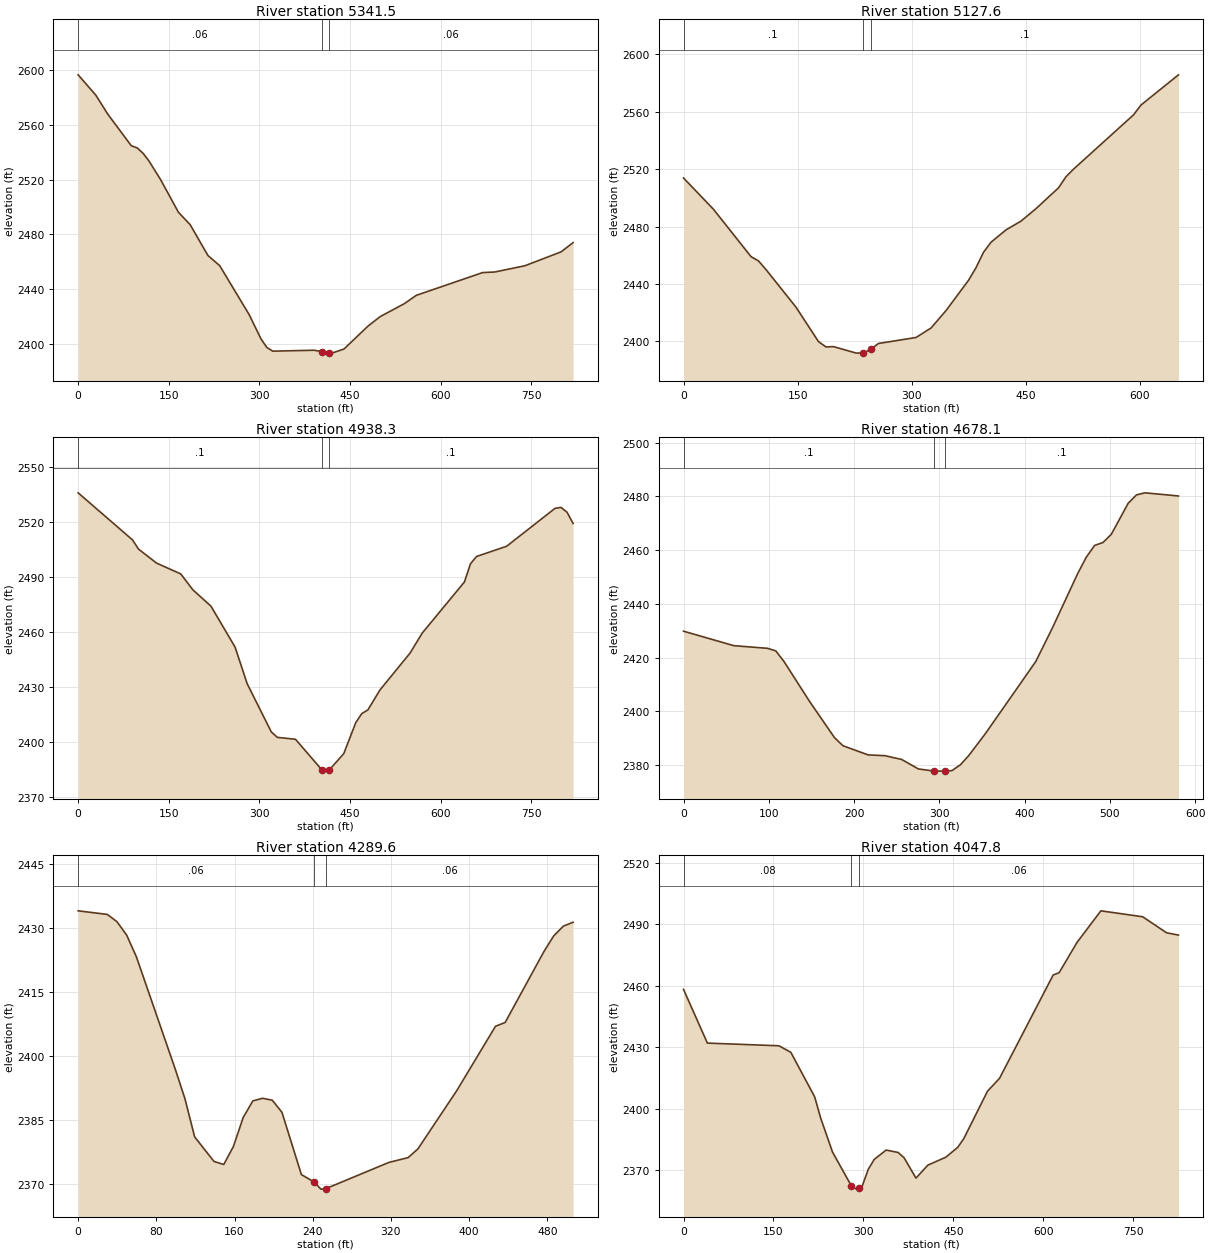
Type RM Length L Ch R = 1 ,5341.5  ,208.5,213.6,219.8
XS GIS Cut Line= 3
     1912727.148      101086.921     1912990.904       100772.99
     1913239.597      100447.773
#Sta/Elev= 30
       0 2596.75    29.3 2581.83    48.8 2568.13    87.9  2544.9    97.6 2543.29
   107.4 2539.38   117.2 2533.74   136.7  2519.9     166 2496.19   185.5 2487.08
   214.8 2464.59   234.3 2457.13   283.1 2421.33   302.6  2403.6   312.4 2397.26
   322.2 2394.57   390.5 2395.25     404 2394.23     416 2393.32     420 2393.13
     440 2396.11   479.9 2412.92   499.9 2419.82   539.8 2429.26   559.8 2435.41
   669.6 2452.06   689.6 2452.48   739.6 2457.05   799.5 2467.22   819.4 2473.97
#Mann= 3 , 0 , 0
       0     .06       0     404    .045       0     416     .06       0
Bank Sta=404,416
XS Rating Curve= 0 ,0
Exp/Cntr=0.3,0.1

Type RM Length L Ch R = 1 ,5127.6  ,184.2,189.2,194.2
XS GIS Cut Line= 2
     1912930.038      101077.832     1913457.911      100696.945
#Sta/Elev= 30
       0 2513.75    39.4 2491.98    88.8 2459.01    98.6 2456.06   108.5    2450
   147.9 2423.88   177.5 2399.92   187.4 2396.18   197.3 2396.42   226.8 2391.96
   235.7  2391.9   236.7 2391.89   246.6  2394.8   256.4  2398.6   305.8 2402.78
   325.5 2409.36   345.2 2421.49   374.8 2442.56   384.6 2451.28   394.5 2462.05
   404.4 2469.07   424.1 2477.65   443.8 2483.75   463.6 2492.44   493.1 2506.88
     503 2514.64   512.9  2519.9   591.8 2557.68   601.6 2564.51   650.9 2585.54
#Mann= 3 , 0 , 0
       0      .1       0   235.7    .045       0   246.6      .1       0
Bank Sta=235.7,246.6
XS Rating Curve= 0 ,0
Exp/Cntr=0.3,0.1

Type RM Length L Ch R = 1 ,4938.3  ,265.2,260.2,255.3
XS GIS Cut Line= 3
     1912826.368      101258.195     1913205.945      101104.535
     1913585.523      100950.876
#Sta/Elev= 30
       0 2535.92    89.9 2510.24    99.9  2505.2   129.8 2497.57   169.8 2491.66
   189.8    2483   219.7 2474.11   259.7 2451.71   279.7 2431.73   319.6 2405.47
   329.6 2402.48   359.6 2401.45   403.5 2384.68   409.5 2384.06   415.5 2384.67
   439.5 2393.61   459.4 2410.54   469.4 2415.47   479.4 2417.45   499.4 2428.34
   549.3 2448.52   569.3 2459.37   639.2 2487.28   649.2 2497.19   659.2 2501.18
   709.1 2506.78     789 2527.43     799 2527.98     809 2525.33     819  2519.2
#Mann= 3 , 0 , 0
       0      .1       0   403.5    .045       0   415.5      .1       0
Bank Sta=403.5,415.5
XS Rating Curve= 0 ,0
Exp/Cntr=0.3,0.1

Type RM Length L Ch R = 1 ,4678.1  ,401.9,388.6,375.4
XS GIS Cut Line= 2
     1913082.137       101506.01     1913556.328      101171.136
#Sta/Elev= 30
       0 2429.87      59 2424.48    98.4  2423.5   108.2 2422.55   118.1 2418.47
   147.6 2403.84   177.1 2390.24     187 2387.24   216.5 2383.83   236.1 2383.54
   255.8 2382.14   275.5  2378.6   294.2  2377.8   295.2 2377.79   306.2 2377.83
   314.9 2377.99   324.7 2380.15   334.5 2383.56   354.2 2391.81   413.2 2418.61
   432.9 2431.24   462.4 2451.37   472.3 2457.36   482.1 2461.77     492 2462.88
   501.8 2465.95   521.5 2477.46   531.3  2480.6   541.2 2481.36   580.5 2480.19
#Mann= 3 , 0 , 0
       0      .1       0   294.2    .045       0   306.2      .1       0
Bank Sta=294.2,306.2
XS Rating Curve= 0 ,0
Exp/Cntr=0.3,0.1

Type RM Length L Ch R = 1 ,4289.6  ,231.6,241.6,244.6
XS GIS Cut Line= 2
     1913506.481      101834.493     1913666.249      101353.911
#Sta/Elev= 30
       0 2433.94    29.8  2433.1    39.7  2431.4    49.6 2428.27    59.6 2423.16
    99.3 2396.91   109.2    2390   119.2 2381.01     139 2375.27     149 2374.56
   158.9  2378.8   168.8 2385.53   178.7 2389.44   188.7 2390.06   198.6 2389.61
   208.5 2386.78   228.4 2372.19   241.6 2370.44   248.3 2368.79   253.6 2368.92
   317.8 2375.03   337.6 2376.17   347.6  2378.2   387.3 2391.82     427 2406.91
   436.9 2407.81   476.6 2424.42   486.6 2428.08   496.5 2430.37   506.4 2431.27
#Mann= 3 , 0 , 0
       0     .06       0   241.6    .045       0   253.6     .06       0
Bank Sta=241.6,253.6
XS Rating Curve= 0 ,0
Exp/Cntr=0.3,0.1

Type RM Length L Ch R = 1 ,4047.8  ,339.9,336.6,333.3
XS GIS Cut Line= 3
     1913589.547      102007.308     1913752.154      101622.644
     1913843.868      101225.017
#Sta/Elev= 30
       0 2458.16    39.8 2431.95   159.1 2430.64     179 2427.46   218.8 2405.72
   228.7 2395.46   248.6 2378.76     280 2362.29   288.4 2360.69     292 2361.29
   298.3 2362.34   308.2 2370.35   318.2 2375.22   338.1 2379.75     358 2378.58
   367.9 2376.01   387.8 2366.07   407.7 2372.42   437.5 2376.25   457.4 2381.05
   467.4 2385.25   507.2 2408.51   527.1 2414.71   616.7 2465.18   626.6 2466.29
   656.5 2481.09   696.3 2496.49     766 2493.59   805.8 2485.79   825.7 2484.64
#Mann= 3 , 0 , 0
       0     .08       0     280    .045       0     292     .06       0
#XS Ineff= 2 , 0
                          338.61         2379.52
Permanent Ineff=
       F       F
Bank Sta=280,292
XS Rating Curve= 0 ,0
Exp/Cntr=0.3,0.1

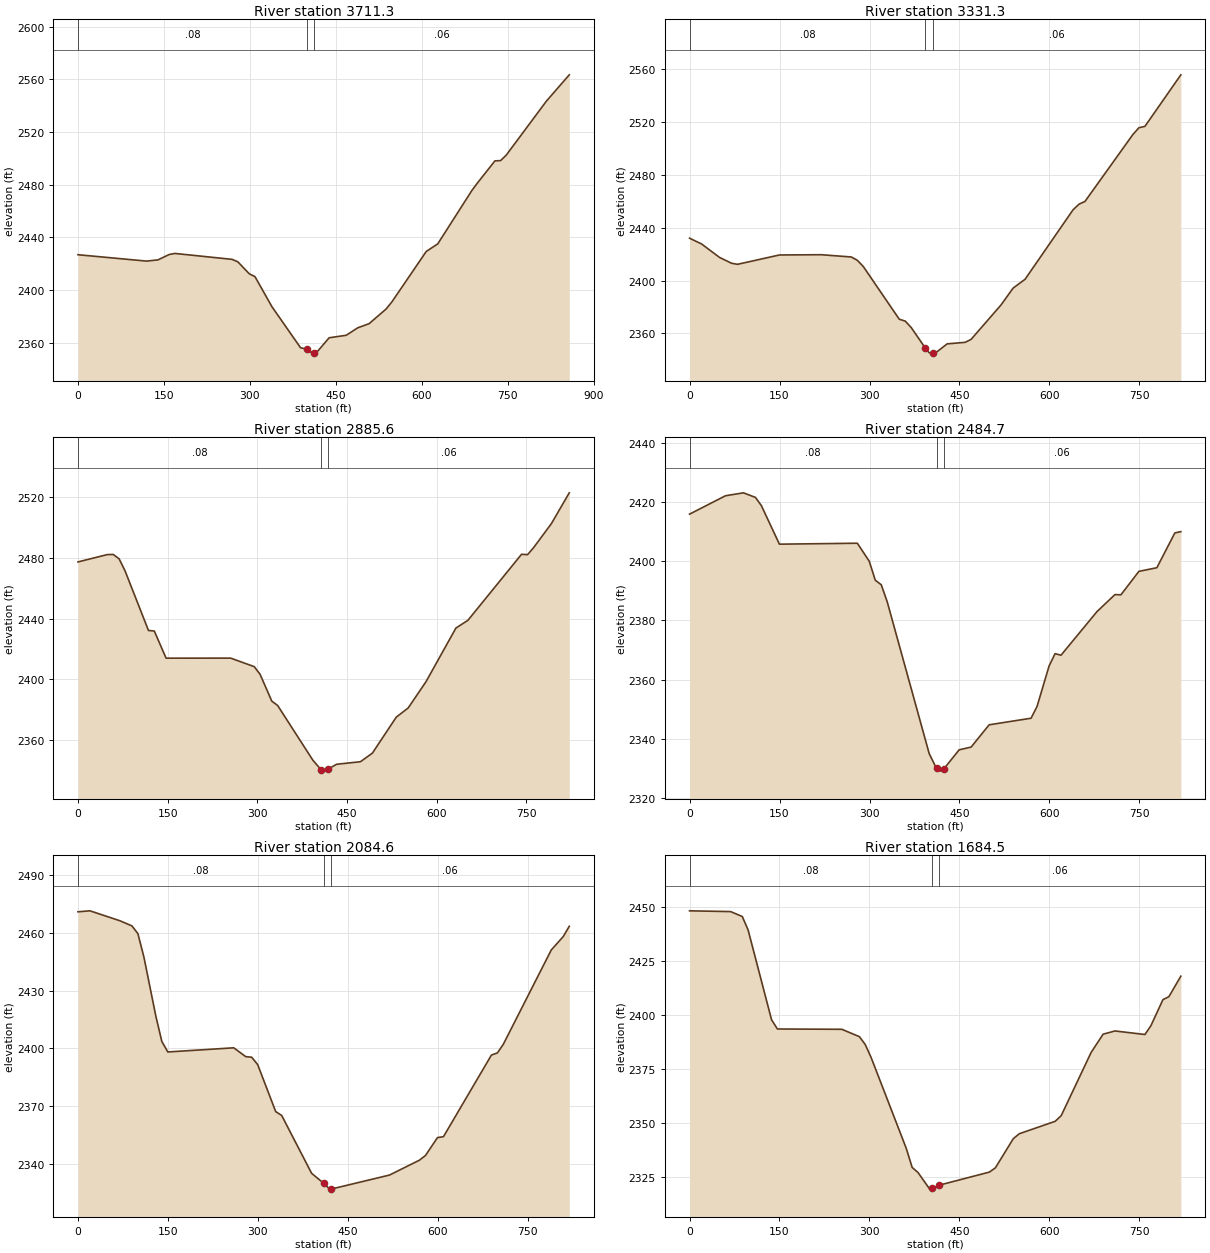
Type RM Length L Ch R = 1 ,3711.3  ,381.7,380,378.3
XS GIS Cut Line= 3
     1913929.768      102206.753     1914059.917      101695.175
      1914266.47      101438.693
#Sta/Elev= 30
       0 2426.77   119.5 2421.93   139.4 2422.83   159.4 2426.97   169.3 2427.74
   268.9 2423.25   278.9 2421.39   298.8  2412.3   308.8 2410.12   338.6 2387.14
   388.4 2356.04   399.2 2355.02   408.4 2351.97   411.2 2352.39   418.3 2353.46
   438.2 2363.64   468.1 2365.55     488 2371.18     508 2374.38   537.8 2385.58
   547.8 2390.97   607.7 2429.29   627.7    2435   687.5 2475.76   697.5 2481.58
   727.5 2498.13   737.4 2498.32   747.4 2502.58   817.3 2543.53   857.2 2563.52
#Mann= 3 , 0 , 0
       0     .08       0   399.2    .045       0   411.2     .06       0
Bank Sta=399.2,411.2
XS Rating Curve= 0 ,0
Exp/Cntr=0.3,0.1

Type RM Length L Ch R = 1 ,3331.3  ,443.2,445.6,450
XS GIS Cut Line= 3
     1914335.797      102276.044     1914404.872      101872.412
     1914473.947       101468.78
#Sta/Elev= 30
       0 2432.04      20  2427.7    49.9 2417.51    69.9  2413.1    79.9 2412.26
   149.8 2419.33   219.7 2419.53   269.7 2417.81   279.7  2415.3   289.6 2410.62
   349.6 2370.72   359.6 2369.28   369.6 2364.36     393 2348.89   399.5  2345.3
     405 2345.16   409.5 2345.05   429.5 2352.06   459.4 2353.22   469.4 2355.49
   519.4  2381.6   539.3 2394.22   559.3 2400.94   639.2 2453.46   649.2 2457.77
   659.2 2459.87   739.1 2510.53   749.1 2515.63   759.1 2516.67     819 2555.68
#Mann= 3 , 0 , 0
       0     .08       0     393    .045       0     405     .06       0
Bank Sta=393,405
XS Rating Curve= 0 ,0
Exp/Cntr=0.3,0.1

Type RM Length L Ch R = 1 ,2885.6  ,402,400.8,397.7
XS GIS Cut Line= 3
     1914725.813       102352.75     1914839.853      101956.173
     1914989.797      101575.443
#Sta/Elev= 30
       0 2477.26    49.1  2482.1      59 2482.18    68.8 2479.31    78.6 2471.51
   117.9 2432.15   127.7 2431.75   147.4 2413.89   255.4 2413.92   294.8 2408.32
   304.6 2403.28   324.2  2385.6     334 2382.74     393 2346.65   406.6 2340.47
   412.6 2339.51   418.6 2340.89   432.6 2344.03   472.5  2345.7   492.5 2351.38
   532.4 2375.06   552.4 2381.12   582.3  2398.5   632.2 2433.73   652.2 2438.79
     742 2482.31     752 2482.04     762  2486.6   791.9 2502.49   821.8 2522.76
#Mann= 3 , 0 , 0
       0     .08       0   406.6    .045       0   418.6     .06       0
Bank Sta=406.6,418.6
XS Rating Curve= 0 ,0
Exp/Cntr=0.3,0.1

Type RM Length L Ch R = 1 ,2484.7  ,400,400.1,400.1
XS GIS Cut Line= 3
     1915136.951      102443.096     1915228.643      102043.993
     1915320.335      101644.891
#Sta/Elev= 30
       0 2415.83    59.9 2422.04    89.9 2423.03   109.9 2421.48   119.8 2418.69
   149.8  2405.7   279.7 2406.02   299.6 2399.93   309.6 2393.54   319.6    2392
   329.6 2386.19   399.5 2335.01   411.7 2329.99   419.5  2329.1   423.7  2329.8
   449.4 2336.29   469.4 2337.22   499.4 2344.73   569.3 2346.96   579.3 2350.93
   599.3 2364.56   609.3 2368.75   619.2 2368.22   679.2 2382.94   709.1 2388.68
   719.1 2388.61   749.1 2396.53     779 2397.75     809  2409.5     819 2409.93
#Mann= 3 , 0 , 0
       0     .08       0   411.7    .045       0   423.7     .06       0
Bank Sta=411.7,423.7
XS Rating Curve= 0 ,0
Exp/Cntr=0.3,0.1

Type RM Length L Ch R = 1 ,2084.6  ,398.8,400.1,401.5
XS GIS Cut Line= 3
     1915525.938      102532.501     1915618.479      102133.595
      1915711.02      101734.688
#Sta/Elev= 30
       0 2470.86      20 2471.36    69.9 2466.21    89.9 2463.56    99.9 2459.52
   109.9 2447.41   129.8 2416.78   139.8 2403.63   149.8  2398.2   259.7 2400.35
   279.7 2395.77   289.6 2395.48   299.6 2391.64   329.6 2367.29   339.6 2365.29
   389.5 2335.29     410 2330.04   419.5  2327.1     422 2327.12   519.4  2334.4
   569.3 2342.12   579.3 2344.54   599.3 2353.82   609.3  2354.3   689.2 2396.58
   699.2 2397.71   709.1 2402.22     789 2451.07     809 2458.05     819 2463.35
#Mann= 3 , 0 , 0
       0     .08       0     410    .045       0     422     .06       0
Bank Sta=410,422
XS Rating Curve= 0 ,0
Exp/Cntr=0.3,0.1

Type RM Length L Ch R = 1 ,1684.5  ,400.1,401.3,402.5
XS GIS Cut Line= 3
     1915890.543      102617.275     1916008.131      102223.989
     1916126.931      101832.358
#Sta/Elev= 30
       0 2448.21    68.4 2447.86      88 2445.58    97.7 2439.35   136.8 2397.86
   146.6 2393.56   254.1 2393.42   283.4 2390.01   293.2 2386.34     303 2380.34
   361.6 2338.33   371.4 2329.54   381.2 2327.18   400.7  2319.5   404.5 2319.82
   416.5 2321.33   500.3 2327.38   510.3 2329.36   540.2 2342.86   550.2 2345.12
   610.1 2350.87   620.1 2353.49     670 2382.71     690 2391.16   709.9 2392.65
   759.8 2391.01   769.8  2395.1   789.8 2407.12   799.8 2408.52   819.7 2417.99
#Mann= 3 , 0 , 0
       0     .08       0   404.5    .045       0   416.5     .06       0
Bank Sta=404.5,416.5
XS Rating Curve= 0 ,0
Exp/Cntr=0.3,0.1

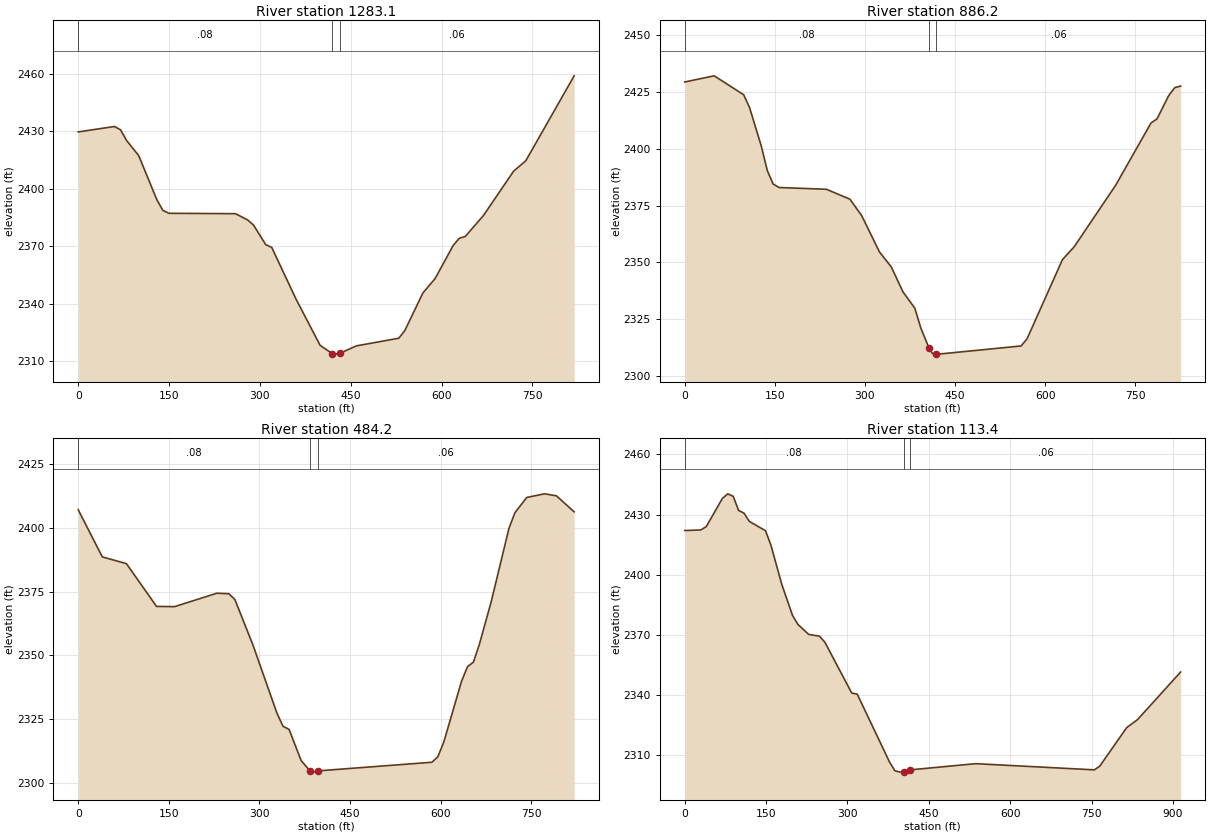
Type RM Length L Ch R = 1 ,1283.1  ,387.8,397,406
XS GIS Cut Line= 3
     1916240.916      102748.255     1916382.751      102364.103
     1916522.709      101979.257
#Sta/Elev= 30
       0 2429.61    59.9 2432.45    69.9 2430.71    79.9 2425.15    99.9 2417.26
   129.8 2394.32   139.8 2388.72   149.8 2387.19   259.7 2386.99   279.7 2383.75
   289.6 2381.02   309.6 2370.88   319.6  2369.4   359.6 2342.53   399.5 2318.34
   419.6 2314.05   429.5 2313.77   431.6 2314.12   459.4 2318.08   529.4 2322.05
   539.3    2326   569.3 2345.69   589.3 2353.13   619.2  2370.4   629.2 2374.15
   639.2 2375.11   669.2 2386.02   719.1 2409.18   739.1 2414.55     819 2458.86
#Mann= 3 , 0 , 0
       0     .08       0   419.6    .045       0   431.6     .06       0
Bank Sta=419.6,431.6
XS Rating Curve= 0 ,0
Exp/Cntr=0.3,0.1

Type RM Length L Ch R = 1 ,886.2   ,414,401.8,389.8
XS GIS Cut Line= 3
       1916437.7      102828.522      1916730.52      102537.949
     1917019.543      102243.117
#Sta/Elev= 30
       0 2429.42    49.1 2432.13    98.2  2423.8     108 2418.14   127.7 2401.03
   137.5 2390.42   147.3 2384.47   157.2 2382.96   235.7 2382.19     275 2377.82
   294.7 2370.53   324.1 2354.63   343.8 2348.04   363.4 2336.98   383.1  2329.8
   392.9 2321.18   406.5 2312.36   412.5 2309.83   418.5 2309.69   422.4  2309.6
     560  2313.2   569.8 2316.33   628.8 2351.23   648.4  2356.9   717.3 2383.95
   776.2 2411.39   786.1 2413.16   805.7 2423.48   815.6 2426.92   825.4 2427.62
#Mann= 3 , 0 , 0
       0     .08       0   406.5    .045       0   418.5     .06       0
Bank Sta=406.5,418.5
XS Rating Curve= 0 ,0
Exp/Cntr=0.3,0.1

Type RM Length L Ch R = 1 ,484.2   ,369.6,370.9,372.4
XS GIS Cut Line= 3
     1916992.297       103108.96      1917078.88      102709.191
     1917149.068      102303.055
#Sta/Elev= 30
       0 2407.03    39.9 2388.56    79.8 2385.92   129.7 2369.17   159.6 2369.08
   229.5 2374.33   249.4 2374.14   259.4 2371.87   289.3 2354.09   329.2 2327.28
   339.2 2322.21   349.2    2321   369.1 2308.82   384.4  2304.6   389.1 2304.27
   396.4 2304.75   585.7 2308.14   595.5 2310.29   605.3 2316.01   634.7 2339.84
   644.6 2345.56   654.4 2347.34   664.2 2354.27   683.8 2370.95   713.2  2399.7
   723.1 2405.85   742.7 2411.84   772.1 2413.26   791.8 2412.49   821.2 2406.21
#Mann= 3 , 0 , 0
       0     .08       0   384.4    .045       0   396.4     .06       0
Bank Sta=384.4,396.4
XS Rating Curve= 0 ,0
Exp/Cntr=0.3,0.1

Type RM Length L Ch R = 1 ,113.4   ,113.6,113.4,113.2
XS GIS Cut Line= 2
     1917325.576      103176.545      1917570.98      102295.903
#Sta/Elev= 30
       0 2422.01    29.8 2422.31    39.8 2423.98    69.6 2438.08    79.5 2440.33
    89.4  2439.1    99.4 2432.06   109.3 2430.69   119.2 2426.55     149 2421.94
     159  2414.7   178.9 2395.24   198.7 2379.72   208.7 2375.18   228.6 2370.19
   248.4  2369.3   258.4 2366.31     308  2340.9     318 2340.41   377.6 2306.52
   387.5 2302.15   397.5 2301.46   403.6 2301.72   415.6 2302.59   536.6 2305.68
   755.2 2302.59   765.1 2304.43   814.8 2323.67   834.7 2327.64   914.2 2351.41
#Mann= 3 , 0 , 0
       0     .08       0   403.6    .045       0   415.6     .06       0
#XS Ineff= 2 , 0
                          536.48         2305.66
Permanent Ineff=
       F       F
Bank Sta=403.6,415.6
XS Rating Curve= 0 ,0
Exp/Cntr=0.3,0.1

Chan Stop Cuts=-1
Use User Specified Reach Order=0
Composite Channel Slope=5